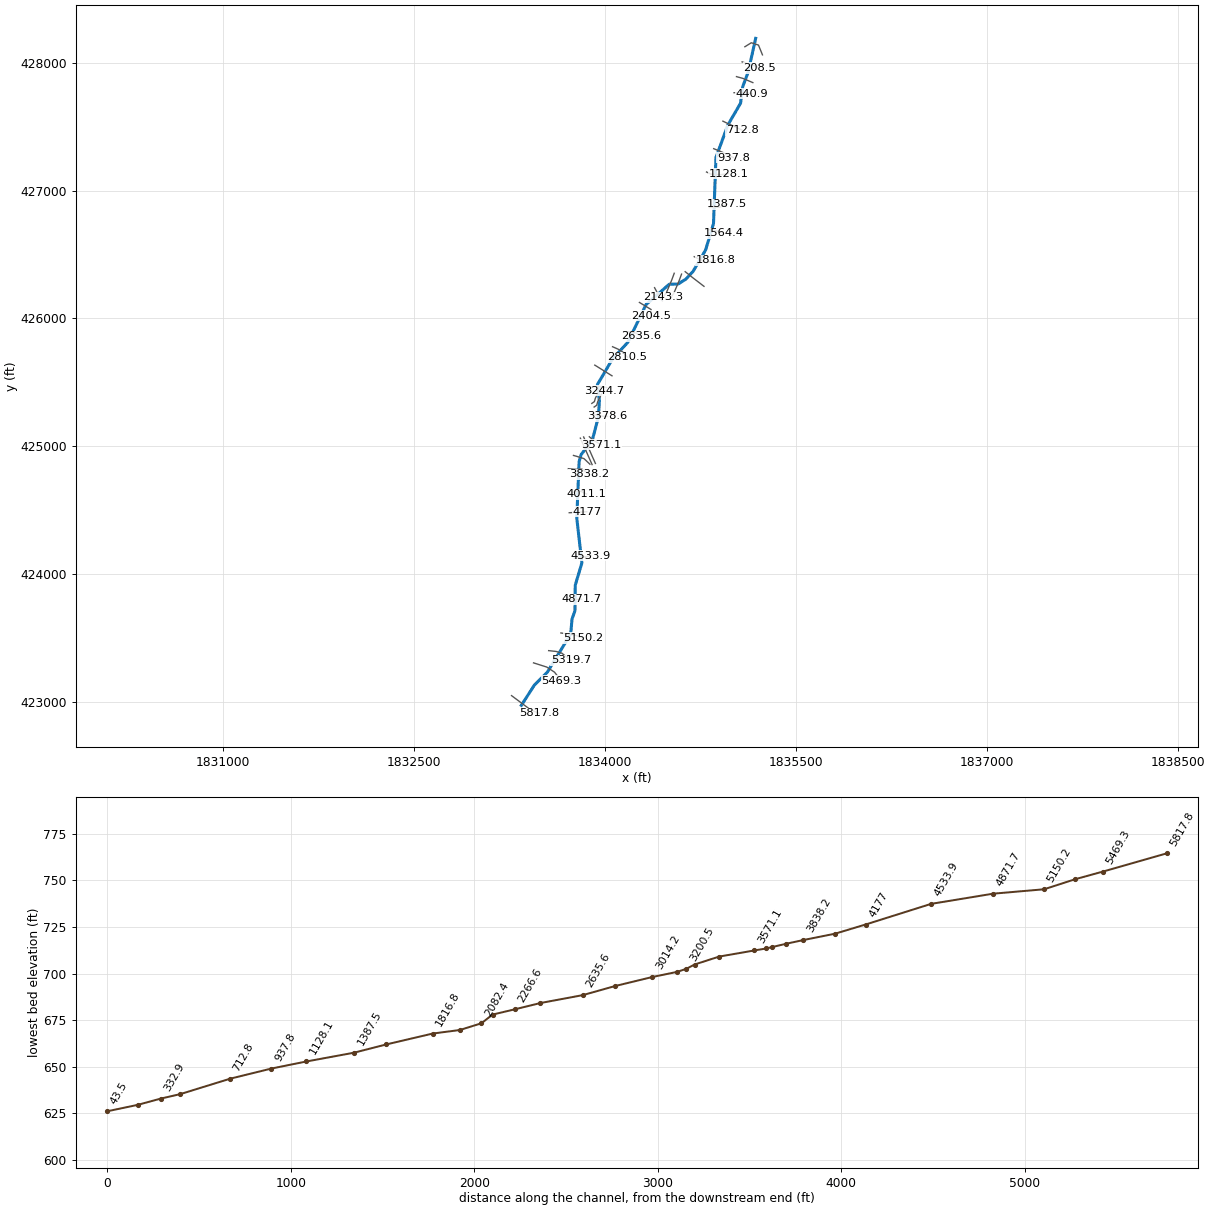
--- WETBRANCH.prj (project) ---

Proj Title=WETBRANCH
Current Plan=p01
Default Exp/Contr=0,0
English Units
Geom File=g01
Flow File=f01
Plan File=p01
BEGIN DESCRIPTION:
END DESCRIPTION:
DSS File=dss
DSS Export Rating Curves= 0
DSS Export Rating Curve Sorted= 0
DSS Export Volume Flow Curves= 0
DXF OffsetX= 0
DXF OffsetY= 0
DXF ScaleX= 0
DXF ScaleY= 0

--- WETBRANCH.p01 (plan) ---

Plan Title=Floodplain
Program Version=4.10
Short Identifier=Floodplain
Geom File=g01
Flow File=f01
Subcritical Flow
K Sum by GR= 0
Std Step Tol= 0.01
Critical Tol= 0.01
Num of Std Step Trials= 20
Max Error Tol= 0.3
Flow Tol Ratio= 0.001
Split Flow NTrial= 30
Split Flow Tol= 0.02
Split Flow Ratio= 0.02
Log Output Level= 0
Friction Slope Method= 1
Unsteady Friction Slope Method= 2
Unsteady Bridges Friction Slope Method= 1
Parabolic Critical Depth
Global Vel Dist= 0 , 0 , 0
Global Log Level= 0
CheckData=True
Encroach Param=-1 ,0,0, 0
Run HTab= 0
Run UNet= 0
Run PostProcess= 0
Run WQNet= 0
UNET Theta= 0
UNET Theta Warmup= 0
UNET ZTol= 0
UNET ZSATol= 0
UNET MxIter= 0
UNET MaxInSteps= 0
UNET DtIC= 0
UNET DtMin= 0
UNET MaxCRTS= 0
UNET WFStab= 0
UNET SFStab= 0
UNET WFX= 1
UNET SFX= 1
UNET DSS MLevel= 1
UNET DZMax Abort= 0
UNET Convert EG Bridges= 0
UNET Use Existing IB Tables= 0
UNET Froude Reduction=False
UNET Froude Limit= 0
UNET Froude Power= 0
UNET Time Slicing=0,0, 5
UNET Junction Losses=0
DSS File=dss
Write IC File= 0
Write IC File at Sim End=0
Echo Input=False
Echo Parameters=False
Echo Output=False
Write Detailed= 0
WQ AD Non Conservative
WQ ULTIMATE=-1
WQ Max Comp Step=1HOUR
WQ Output Interval=15MIN
WQ Output Selected Increments= 0
WQ Output face flow=0
WQ Output face velocity=0
WQ Output face area=0
WQ Output face dispersion=0
WQ Output cell volume=0
WQ Output cell surface area=0
WQ Output cell continuity=0
WQ Output cumulative cell continuity=0
WQ Output face conc=0
WQ Output face dconc_dx=0
WQ Output face courant=0
WQ Output face peclet=0
WQ Output face adv mass=0
WQ Output face disp mass=0
WQ Output cell mass=0
WQ Output cell source sink temp=0
WQ Output cell source sink nsm=0
WQ Output MaxMinRange=-1
WQ Daily Max Min Mean=-1
WQ Daily Range=0
WQ Daily Time=0
WQ Create Restart=0
WQ Fixed Restart=0
WQ System Summary=0
WQ Use Fixed Temperature=0
Sorting and Armoring Iterations= 10
XS Update Threshold= 0.02
Hydraulics Update Threshold= 0.02
Energy Slope Method= 1
Volume Change Method= 0
XS Weighting Method= 0
Number of US Weighted Cross Sections= 1
Number of DS Weighted Cross Sections= 1
Upstream XS Weight=0.25
Main XS Weight=0.5
Downstream XS Weight=0.25
Number of DS XS's Weighted with US Boundary= 1
Upstream Boundary Weight= 1
Weight of XSs Associated with US Boundary= 0
Number of US XS's Weighted with DS Boundary= 1
Downstream Boundary Weight= 0.5
Weight of XSs Associated with DS Boundary= 0.5
Sediment Output Level= 4
Mass or Volume Output= 0
Output Increment Type= 1
Profile and TS Output Increment= 10
XS Output Flag= 0
XS Output Increment= 10
Disregard all LS=0
Disregard all Conn=0
Disregard all Breaches=0
Disregard all Pumps=0

--- WETBRANCH.f01 (steady flow) ---

Flow Title=NFF Regression Equation
Program Version=4.10
Number of Profiles= 1
Profile Names=P100yr
River Rch & RM=WETBRANCH,Main            ,5817.8
886.2355
River Rch & RM=WETBRANCH,Main            ,4533.9
980.8537
River Rch & RM=WETBRANCH,Main            ,3665.1
1042.147
River Rch & RM=WETBRANCH,Main            ,1564.4
1114.931
Boundary for River Rch & Prof#=WETBRANCH,Main            , 1
Up Type= 0
Dn Type= 3
Dn Slope=0.02
DSS Import GetInterval= 0
DSS Import GetPeak= 0
DSS Import FillOption= 0

--- WETBRANCH.g01 (geometry) ---

Geom Title=USGS 10m DEM
Program Version=4.10

River Reach=WETBRANCH       ,Main
Reach XY= 30
     1833342.357      422974.592     1833445.438      423134.097
      1833546.35      423233.923     1833729.726      423532.318
     1833740.309      423649.526     1833763.364      423714.609
     1833765.641      423914.287     1833817.617      424087.873
     1833777.469      424439.436     1833795.916      424879.974
     1833811.107      424934.227     1833900.082       425050.33
      1833946.74      425227.196     1833955.421      425355.234
     1833939.145      425482.187     1834057.417       425681.84
     1834177.557        425812.5     1834322.174      426109.357
     1834503.946      426267.361      1834573.39      426269.097
     1834634.154      426307.291      1834689.71      426366.319
     1834789.188      426535.095     1834851.168      426741.099
     1834870.364       427258.54     1834964.188      427512.873
     1835063.494      427682.318      1835080.16      427811.484
     1835122.781      427923.882     1835182.244      428189.956

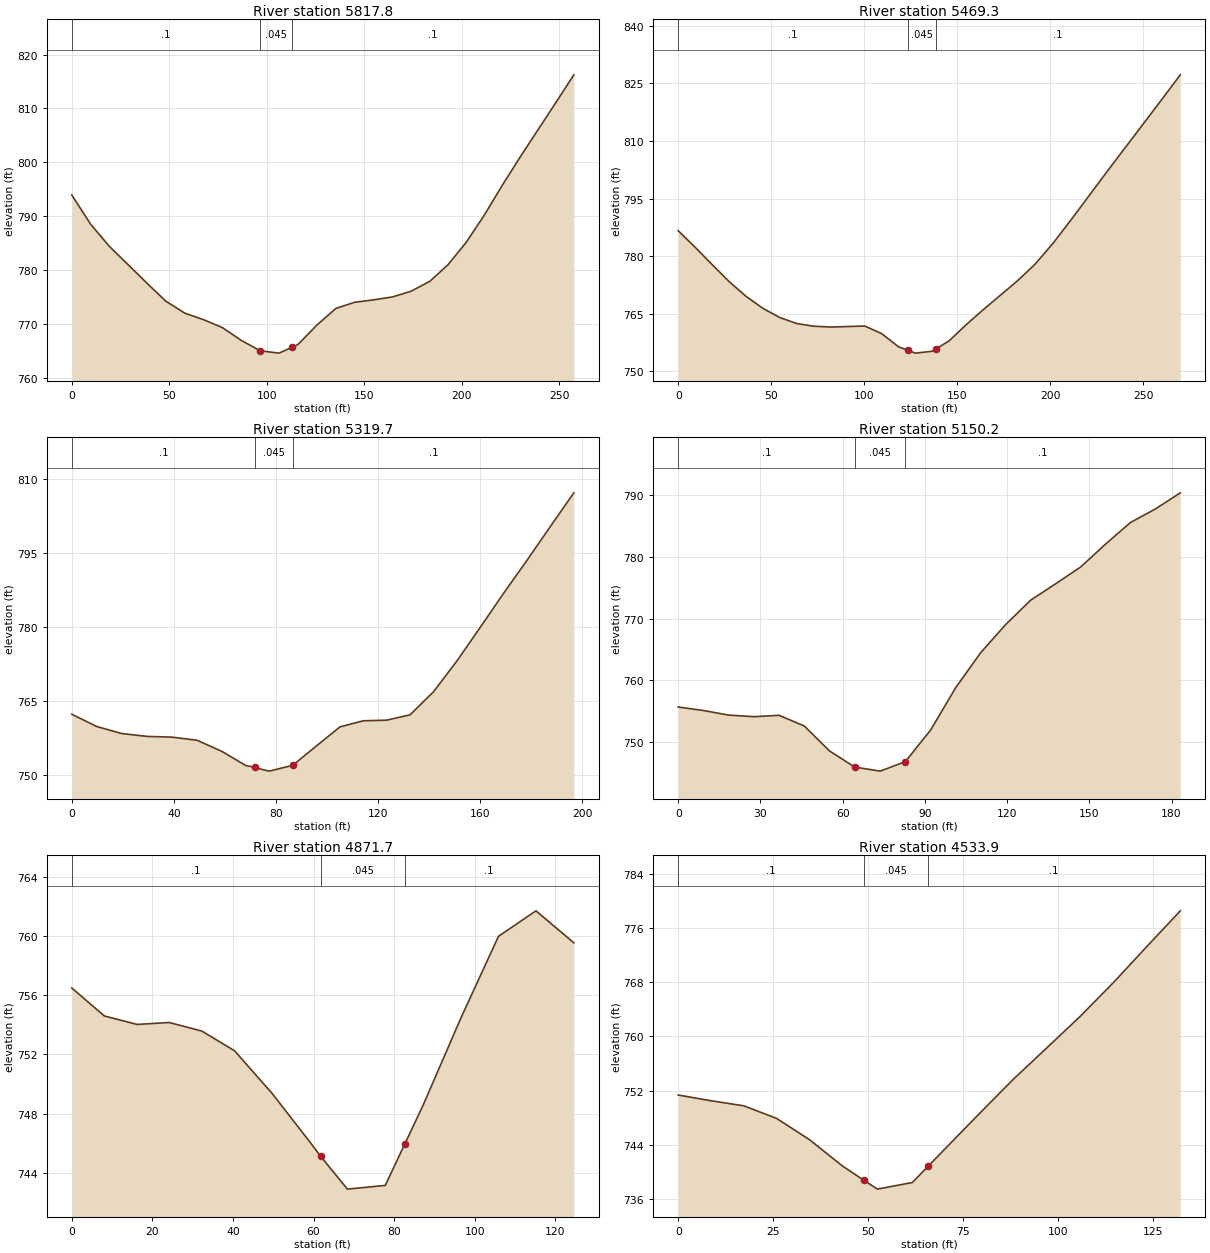
Type RM Length L Ch R = 1 ,5817.8  ,346.8,348.5,349.7
XS GIS Cut Line= 3
       1833265.2      423050.635     1833412.769       422941.26
     1833480.477      422911.746
#Sta/Elev= 30
       0  793.92     9.7  788.48    19.3  784.37      29  780.94    38.7  777.49
    48.3  774.18      58  771.97    67.7  770.75    77.3  769.28      87   766.9
    96.7  764.98    98.2  764.91   106.3  764.55   113.2  765.68     116  766.14
   125.7  769.75   135.4  772.84     145  773.99   154.7  774.44   164.4  774.98
     174  776.04   183.7   777.9   192.9  780.94   202.2  785.08   211.4  790.07
   220.6   795.6   229.8  800.87   239.1  806.01   248.3  811.09   257.5  816.23
#Mann= 3 , 0 , 0
       0      .1       0    96.7    .045       0   113.2      .1       0
Bank Sta=96.7,113.2
XS Rating Curve= 0 ,0
Exp/Cntr=0.3,0.1

Type RM Length L Ch R = 1 ,5469.3  ,143.3,149.5,156
XS GIS Cut Line= 4
     1833437.943      423306.711     1833542.109      423273.725
     1833602.873      423233.794     1833656.693       423164.35
#Sta/Elev= 27
       0   786.6     9.1  782.31    18.2   777.8    27.3  773.39    36.4  769.55
    45.5   766.4    54.6     764    63.7  762.44    72.8  761.75      82  761.53
   100.2   761.8   109.3  759.83   118.4  756.39   123.3  755.49   127.4  754.74
   136.5  755.22   138.3  755.76   145.6  757.95   154.7  762.13   163.8  766.01
     182  773.44   191.7  777.87   201.5   783.4   211.3  789.58   230.8  802.25
   260.1  820.95   269.8  827.21
#Mann= 3 , 0 , 0
       0      .1       0   123.3    .045       0   138.3      .1       0
Bank Sta=123.3,138.3
XS Rating Curve= 0 ,0
Exp/Cntr=0.3,0.1

Type RM Length L Ch R = 1 ,5319.7  ,165.9,169.5,172.8
XS GIS Cut Line= 4
     1833556.758      423402.414     1833615.352      423395.904
     1833659.622      423382.883     1833731.237      423325.591
#Sta/Elev= 25
       0  762.24     9.8  759.74    19.6  758.32    29.5  757.74    39.3  757.59
    49.1  756.96      59  754.66    68.2  751.83   71.74  751.45    74.4  751.06
    77.4  750.69    86.6  751.86    89.4  753.05    95.9   755.8   105.1  759.66
   114.3  760.91   123.4  761.03   132.6  762.12   141.8   766.8     151  773.08
   160.1  779.86   169.3  786.81   178.5  793.53   187.6  800.35   196.8  807.18
#Mann= 3 , 0 , 0
       0      .1       0   71.74    .045       0    86.6      .1       0
Bank Sta=71.74,86.6
XS Rating Curve= 0 ,0
Exp/Cntr=0.3,0.1

Type RM Length L Ch R = 1 ,5150.2  ,275,278.5,281.7
XS GIS Cut Line= 4
     1833653.112      423540.435     1833707.799      423532.622
     1833753.372      423526.112     1833831.497      423501.372
#Sta/Elev= 23
       0  755.68     9.2  755.11    18.4  754.37    27.6  754.11    36.8  754.33
      46   752.6    55.2  748.56    64.4  745.95      69  745.62    73.7  745.29
    82.9  746.84      84  747.45    92.1  751.95   101.3  758.85   110.4   764.5
   119.5  769.05   128.6  772.99   137.7  775.64   146.8  778.35   155.9  782.06
     165  785.57   174.1  787.76   183.2  790.38
#Mann= 3 , 0 , 0
       0      .1       0    64.4    .045       0    82.9      .1       0
Bank Sta=64.4,82.9
XS Rating Curve= 0 ,0
Exp/Cntr=0.3,0.1

Type RM Length L Ch R = 1 ,4871.7  ,335.2,337.8,341.4
XS GIS Cut Line= 3
     1833695.422      423819.947     1833731.881      423802.586
     1833816.082      423803.454
#Sta/Elev= 18
       0  756.49     8.1   754.6    16.2  754.03    24.2  754.16    32.3  753.58
    40.4  752.25    49.7  749.38    59.1  746.09   61.75  745.13    67.6  743.18
    68.4  742.91    77.8  743.16    82.6  745.93    87.2  748.58    96.5  754.42
   105.9  759.98   115.2   761.7   124.6  759.54
#Mann= 3 , 0 , 0
       0      .1       0   61.75    .045       0    82.6      .1       0
Bank Sta=61.75,82.6
XS Rating Curve= 0 ,0
Exp/Cntr=0.3,0.1

Type RM Length L Ch R = 1 ,4533.9  ,358.2,357,354.1
XS GIS Cut Line= 4
     1833758.581       424125.07     1833801.549      424128.977
     1833828.893      424132.883     1833888.789      424145.904
#Sta/Elev= 19
       0  751.34     8.6   750.5    17.3  749.74    25.9  747.88    34.5  744.76
    43.2  740.86   48.86  738.74    50.7  738.07    52.4  737.44    61.6  738.42
    65.7  740.79    70.8  743.74    79.5  748.75    88.3  753.74      97  758.32
   105.8  762.98   114.6  768.01   123.3  773.28   132.1  778.55
#Mann= 3 , 0 , 0
       0      .1       0   48.86    .045       0    65.7      .1       0
Bank Sta=48.86,65.7
XS Rating Curve= 0 ,0
Exp/Cntr=0.3,0.1

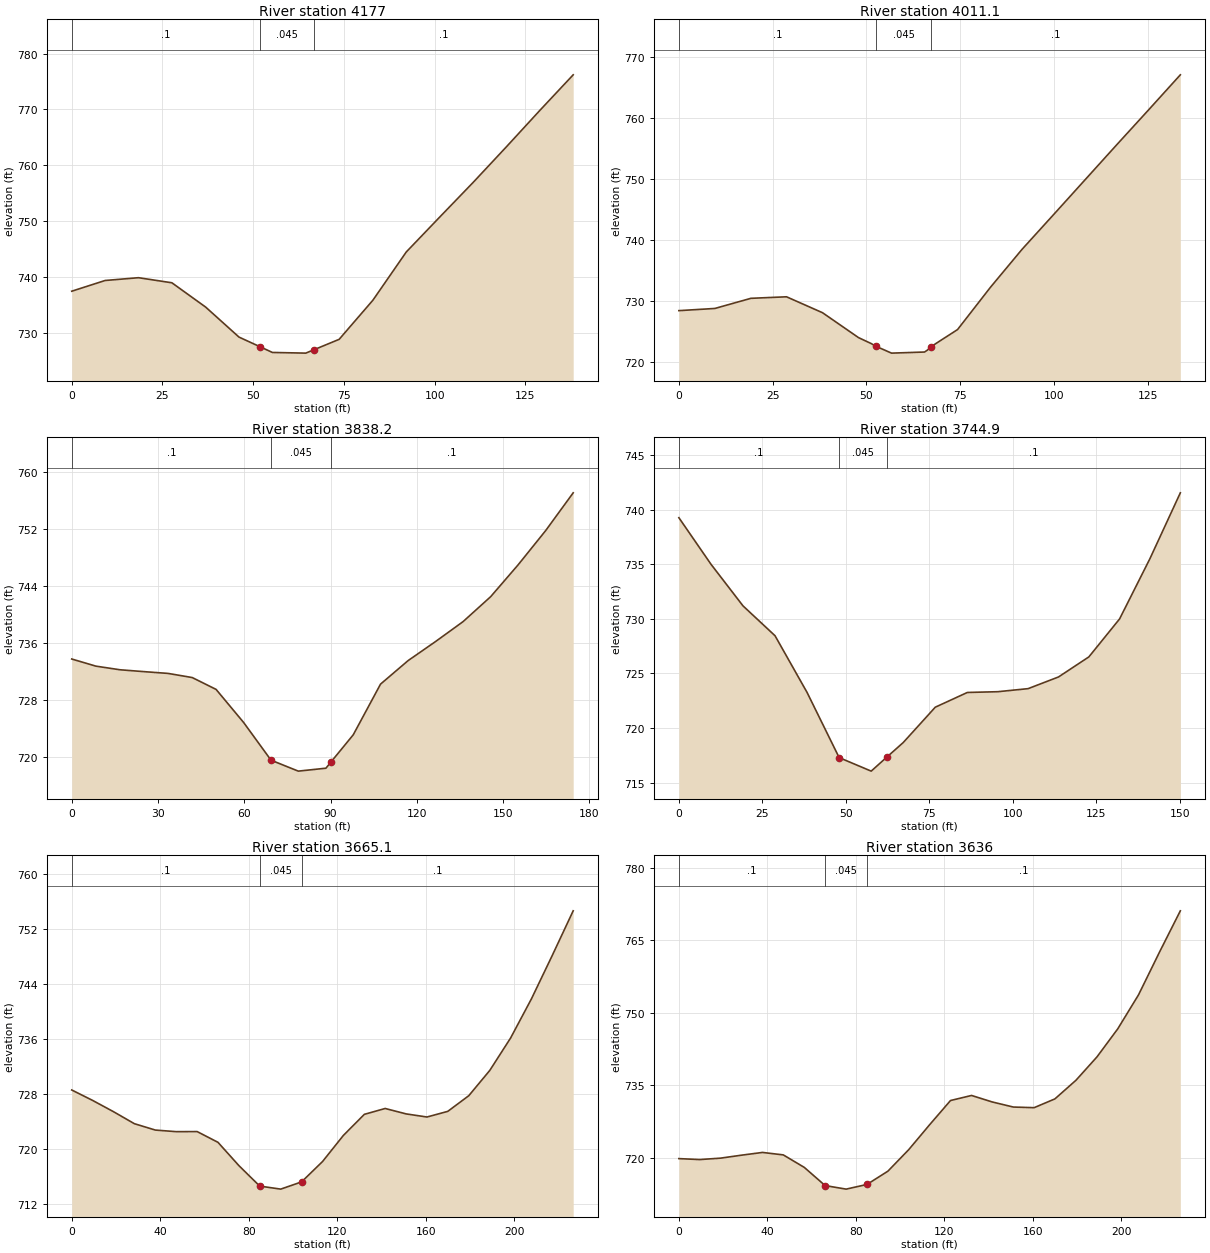
Type RM Length L Ch R = 1 ,4177    ,162.2,165.9,163.8
XS GIS Cut Line= 2
     1833718.216      424480.539     1833856.237      424488.352
#Sta/Elev= 18
       0  737.45     9.2  739.37    18.4  739.87    27.6  738.96    36.9  734.61
    46.1  729.23    51.8  727.53    55.3  726.48    64.5  726.36    66.8  726.98
    73.7  728.83      83  735.84    92.2  744.48   101.4  750.72   110.6  756.92
   119.8  763.32     129  769.83   138.2  776.21
#Mann= 3 , 0 , 0
       0      .1       0    51.8    .045       0    66.8      .1       0
Bank Sta=51.8,66.8
XS Rating Curve= 0 ,0
Exp/Cntr=0.3,0.1

Type RM Length L Ch R = 1 ,4011.1  ,177.1,172.9,174.2
XS GIS Cut Line= 4
     1833729.935      424631.581     1833774.206       424649.81
     1833809.362      424648.508     1833854.935      424626.372
#Sta/Elev= 20
       0   728.4     9.6  728.76    19.2  730.42    28.7  730.67    38.3  728.06
    47.9  723.98    51.3     723   52.58  722.55    56.7  721.44    65.5  721.62
    66.3  721.95   67.21  722.49    74.3   725.3    83.1  732.25    91.5  738.45
     100   744.2   108.4  749.91   116.8  755.62   125.3  761.34   133.7  767.04
#Mann= 3 , 0 , 0
       0      .1       0   52.58    .045       0   67.21      .1       0
Bank Sta=52.58,67.21
XS Rating Curve= 0 ,0
Exp/Cntr=0.3,0.1

Type RM Length L Ch R = 1 ,3838.2  ,100.6,93.3,85.7
XS GIS Cut Line= 4
     1833711.308      424825.155     1833761.308      424820.294
     1833818.477      424821.685     1833871.862       424781.32
#Sta/Elev= 22
       0  733.74     8.4  732.74    16.8  732.23    25.1  731.97    33.5  731.72
    41.9  731.14    50.2  729.48    59.8  724.83    69.3  719.56    75.2   718.6
    78.8  718.02    88.4  718.43    90.2  719.32    97.9  723.11   107.4  730.22
     117  733.52   126.5  736.18   136.1  738.98   145.7  742.48   155.2  746.92
   164.8  751.73   174.4  757.04
#Mann= 3 , 0 , 0
       0      .1       0    69.3    .045       0    90.2      .1       0
Bank Sta=69.3,90.2
XS Rating Curve= 0 ,0
Exp/Cntr=0.3,0.1

Type RM Length L Ch R = 1 ,3744.9  ,99.3,79.8,59.1
XS GIS Cut Line= 4
     1833751.586      424928.627     1833788.529      424918.091
     1833834.225      424903.627     1833880.752      424859.877
#Sta/Elev= 19
       0  739.28     9.6  735.02    19.2   731.2    28.8  728.46    38.4  723.26
    47.2  717.79      48  717.29    57.6  716.05    62.2  717.31    67.2  718.67
    76.8  721.91    86.4  723.26    95.5  723.33   104.6  723.61   113.7  724.68
   122.8  726.52     132     730   141.1  735.53   150.2  741.56
#Mann= 3 , 0 , 0
       0      .1       0      48    .045       0    62.2      .1       0
Bank Sta=48,62.2
XS Rating Curve= 0 ,0
Exp/Cntr=0.3,0.1

Type RM Length L Ch R = 1 ,3665.1  ,29.1,29.1,30.4
XS GIS Cut Line= 2
     1833805.456      425063.872     1833897.904      424856.841
#Sta/Elev= 27
       0  728.61     9.4   727.1    18.9  725.45    28.3  723.71    37.8  722.78
    47.2  722.55    56.7  722.56    66.1     721    75.6   717.6      81  715.89
      85  714.63    94.5  714.19      96  714.36   103.9  715.24   113.4  718.21
   122.8     722   132.3  725.07   141.7  725.92   151.2  725.13   160.6  724.68
     170   725.5   179.5  727.78     189  731.46   198.4  736.17   207.8  741.85
   217.3  748.22   226.7  754.67
#Mann= 3 , 0 , 0
       0      .1       0      85    .045       0   103.9      .1       0
Bank Sta=85,103.9
XS Rating Curve= 0 ,0
Exp/Cntr=0.3,0.1

Type RM Length L Ch R = 1 ,3636    ,53.8,64.9,76.7
XS GIS Cut Line= 2
     1833831.497      425072.987     1833923.945      424865.956
#Sta/Elev= 27
       0  719.82     9.4  719.62    18.9  719.92    28.3  720.53    37.8   721.1
    47.2  720.59    56.7     718    66.1  714.24    69.3  713.99    75.6   713.5
    84.3  714.39      85  714.46    94.5  717.22   103.9  721.67   113.4  726.86
   122.8  731.85   132.3   732.9   141.7  731.55   151.2   730.5   160.6  730.37
     170  732.19   179.5  736.04     189  740.88   198.4  746.69   207.8  753.74
   217.3  762.61   226.7  771.14
#Mann= 3 , 0 , 0
       0      .1       0    66.1    .045       0      85      .1       0
Bank Sta=66.1,85
XS Rating Curve= 0 ,0
Exp/Cntr=0.3,0.1

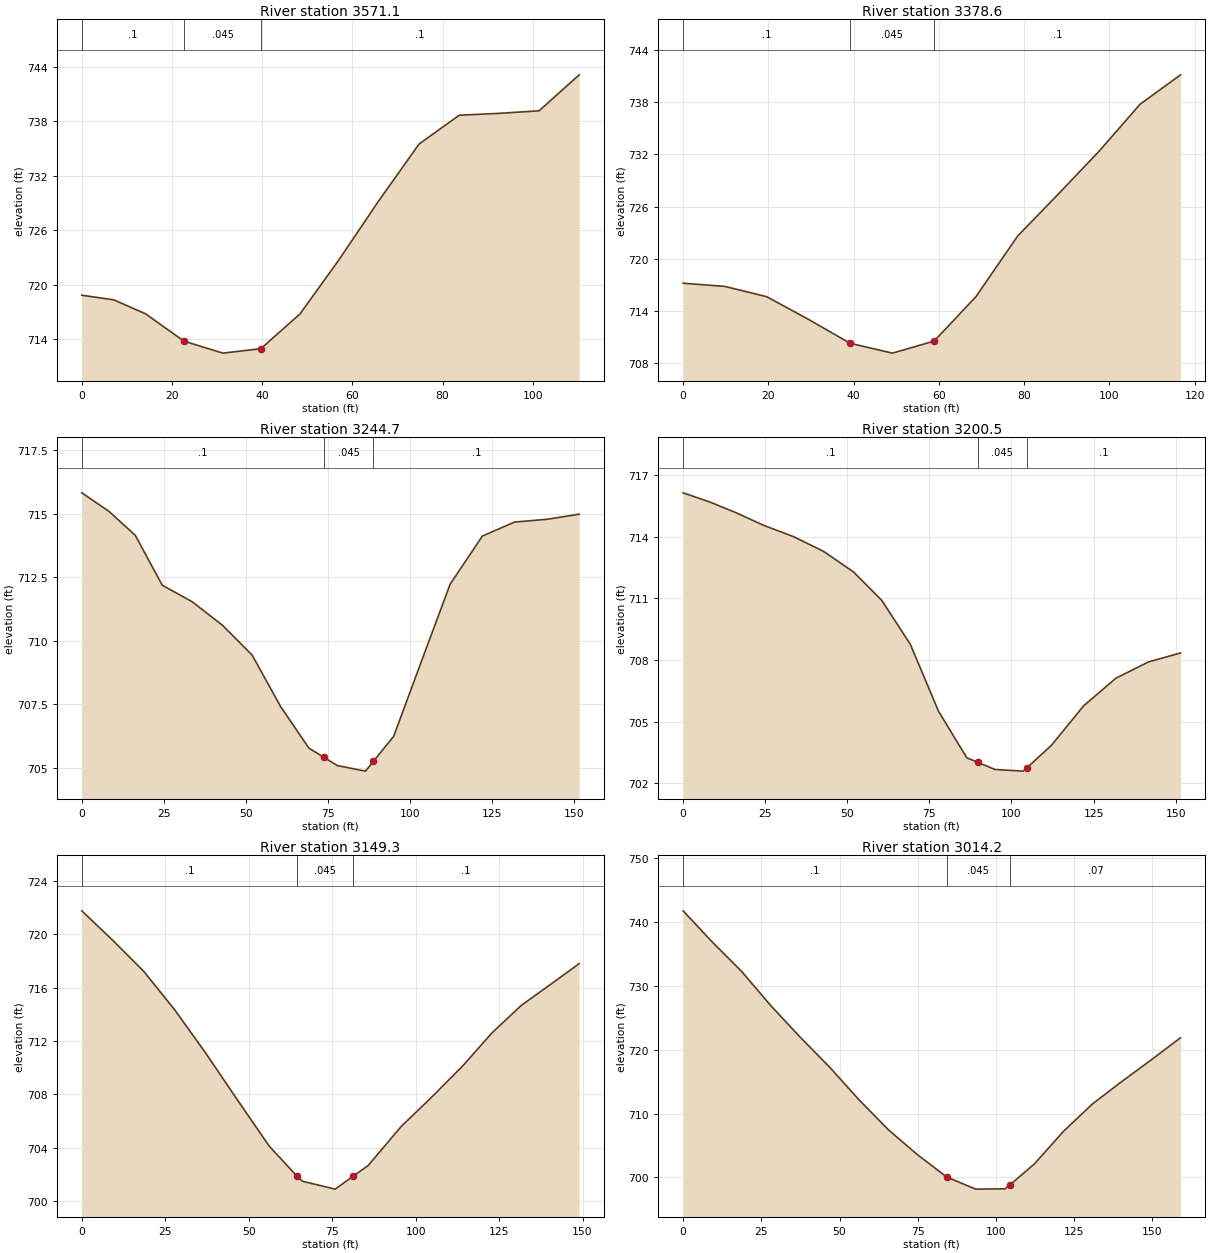
Type RM Length L Ch R = 1 ,3571.1  ,181.1,192.6,202.8
XS GIS Cut Line= 4
     1833876.202      425074.645     1833886.619      425065.096
     1833921.341      425039.923     1833967.348      425013.013
#Sta/Elev= 15
       0  718.82     7.1  718.31    14.1  716.78    22.7  713.74    24.7  713.44
    31.3  712.43    39.7  712.92    48.4  716.76      57  722.71    65.9  729.27
    74.8  735.51    83.7  738.68    92.6  738.89   101.4  739.17   110.3  743.14
#Mann= 3 , 0 , 0
       0      .1       0    22.7    .045       0    39.7      .1       0
Bank Sta=22.7,39.7
XS Rating Curve= 0 ,0
Exp/Cntr=0.3,0.1

Type RM Length L Ch R = 1 ,3378.6  ,74.4,133.8,170.1
XS GIS Cut Line= 3
     1833902.244      425249.124     1833979.501      425235.235
     1834017.695      425233.499
#Sta/Elev= 14
       0  717.18     9.8  716.81    19.6  715.63    29.4  713.02    39.2  710.26
    49.1  709.13    54.2  709.85    58.9  710.52    68.7  715.63    78.5  722.62
      88  727.43    97.6  732.38   107.2  737.78   116.7  741.17
#Mann= 3 , 0 , 0
       0      .1       0    39.2    .045       0    58.9      .1       0
Bank Sta=39.2,58.9
XS Rating Curve= 0 ,0
Exp/Cntr=0.3,0.1

Type RM Length L Ch R = 1 ,3244.7  ,68.2,44.2,45.6
XS GIS Cut Line= 5
     1833913.709      425306.969     1833933.848      425320.858
     1833941.487      425347.247     1833967.876      425401.414
     1833988.709      425434.747
#Sta/Elev= 20
       0  715.82     8.2   715.1    16.3  714.15    24.5  712.19    33.6  711.54
    42.8  710.62    51.9  709.44    60.5  707.43    69.2  705.78    73.8  705.42
    77.8   705.1    86.4  704.88    88.8  705.26      95  706.25   103.6  709.25
   112.2  712.23     122  714.12   131.8  714.67   141.7  714.78   151.5  714.98
#Mann= 3 , 0 , 0
       0      .1       0    73.8    .045       0    88.8      .1       0
Bank Sta=73.8,88.8
XS Rating Curve= 0 ,0
Exp/Cntr=0.3,0.1

Type RM Length L Ch R = 1 ,3200.5  ,82.2,51.2,17.7
XS GIS Cut Line= 5
     1833895.654      425335.442     1833915.793       425349.33
     1833923.432      425375.719     1833949.821      425429.886
     1833970.654      425463.219
#Sta/Elev= 20
       0  716.14     8.2  715.69    16.3  715.16    24.5  714.56    33.6  714.01
    42.8  713.29    51.9  712.29    60.5  710.91    69.2  708.77    77.8  705.51
    86.4  703.25    89.7  703.03      95  702.68   103.6   702.6   104.7  702.76
   112.2  703.86     122  705.78   131.8  707.12   141.7  707.91   151.5  708.35
#Mann= 3 , 0 , 0
       0      .1       0    89.7    .045       0   104.7      .1       0
Bank Sta=89.7,104.7
XS Rating Curve= 0 ,0
Exp/Cntr=0.3,0.1

Type RM Length L Ch R = 1 ,3149.3  ,148,135.1,122.1
XS GIS Cut Line= 4
     1833866.169      425458.488     1833911.793      425467.006
      1833970.82      425467.874     1834013.355      425458.326
#Sta/Elev= 20
       0  721.74     9.3  719.53    18.6   717.2    27.8  714.34    37.1   711.1
    46.4  707.67    56.2  704.11   64.48  701.88    66.1   701.5    66.3  701.49
    75.9  700.91    81.3  701.88    85.8  702.68    95.6  705.58   105.4  707.94
   114.2  710.16   122.9  712.61   131.6  714.65   140.3  716.21     149  717.79
#Mann= 3 , 0 , 0
       0      .1       0   64.48    .045       0    81.3      .1       0
Bank Sta=64.48,81.3
XS Rating Curve= 0 ,0
Exp/Cntr=0.3,0.1

Type RM Length L Ch R = 1 ,3014.2  ,202.3,203.7,204
XS GIS Cut Line= 2
     1833918.947      425634.877     1834054.154      425551.208
#Sta/Elev= 21
       0  741.79     9.4  736.86    18.7  732.29    28.1  726.89    37.4  721.99
    46.8   717.3    56.1  712.23    65.5  707.52    74.8   703.6    84.2  700.08
    86.8  699.54    93.5  698.16   101.8   698.2   102.9   698.2  104.59  698.88
   112.2  702.07   121.6  707.23   130.9  711.54   140.3  715.06   149.6  718.41
     159   721.9
#Mann= 3 , 0 , 0
       0      .1       0    84.2    .045       0  104.59     .07       0
Bank Sta=84.2,104.59
XS Rating Curve= 0 ,0
Exp/Cntr=0.3,0.1

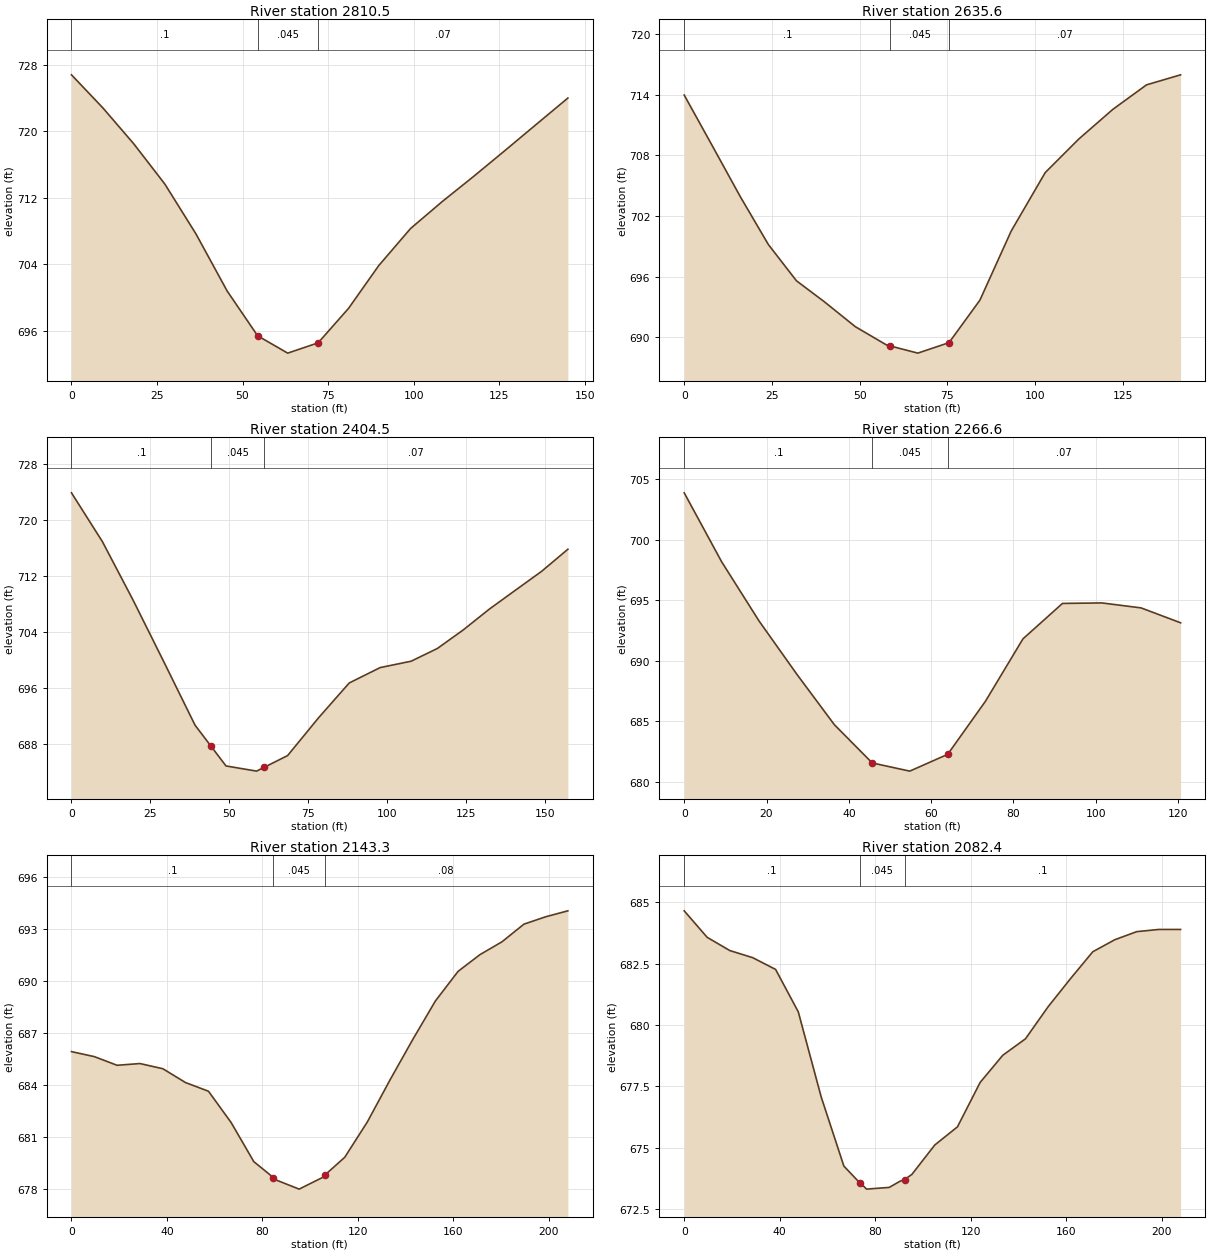
Type RM Length L Ch R = 1 ,2810.5  ,168.6,175,182.4
XS GIS Cut Line= 4
     1834058.494      425778.638     1834100.161      425760.409
     1834138.355       425737.84     1834175.681      425697.041
#Sta/Elev= 19
       0  726.83     9.1  722.88    18.2  718.52    27.3  713.66    36.4  707.65
    45.5  700.78    54.4  695.39    56.1  694.98    63.2  693.29    71.1  694.39
    72.1  694.53      81  698.69    89.8  703.83    99.1   708.3   108.3  711.53
   117.5  714.57   126.7   717.7   135.9  720.87   145.1  724.03
#Mann= 3 , 0 , 0
       0      .1       0    54.4    .045       0    72.1     .07       0
Bank Sta=54.4,72.1
XS Rating Curve= 0 ,0
Exp/Cntr=0.3,0.1

Type RM Length L Ch R = 1 ,2635.6  ,238.6,231.1,223.7
XS GIS Cut Line= 4
     1834150.508      425895.826     1834190.438      425895.826
     1834242.522      425884.541     1834284.188      425860.235
#Sta/Elev= 19
       0  713.95       8  708.94      16   703.9      24  699.17      32  695.59
    39.9  693.53    48.8  691.05    57.7  689.24    58.8  689.14    66.6  688.44
    73.8  689.28    75.5  689.48    84.3  693.68    93.2   700.5   102.9  706.28
   112.5  709.61   122.2  712.54   131.8  714.96   141.5  715.95
#Mann= 3 , 0 , 0
       0      .1       0    58.8    .045       0    75.5     .07       0
Bank Sta=58.8,75.5
XS Rating Curve= 0 ,0
Exp/Cntr=0.3,0.1

Type RM Length L Ch R = 1 ,2404.5  ,151,137.8,124.2
XS GIS Cut Line= 3
     1834269.431      426124.992     1834361.445      426069.437
     1834364.918      426019.958
#Sta/Elev= 21
       0  723.94     9.8  716.96    19.5  708.61    29.3  699.74    39.1  690.76
    44.2  687.73    48.9  684.93    58.6  684.19    59.2  684.33   60.94  684.72
    68.4  686.41    78.2  691.81    87.9  696.78    97.7  698.98   107.5  699.89
   115.8  701.71     124  704.36   132.3  707.35   140.6  710.06   148.8  712.73
   157.1  715.88
#Mann= 3 , 0 , 0
       0      .1       0    44.2    .045       0   60.94     .07       0
Bank Sta=44.2,60.94
XS Rating Curve= 0 ,0
Exp/Cntr=0.3,0.1

Type RM Length L Ch R = 1 ,2266.6  ,143.5,123.3,90.7
XS GIS Cut Line= 4
     1834388.355      426240.444     1834405.716      426208.326
     1834424.813      426166.659     1834449.119      426137.145
#Sta/Elev= 16
       0  703.86     9.1  698.16    18.2  693.26    27.4  688.85    36.5  684.69
    45.7  681.53    46.7  681.46    54.8  680.86    61.7   681.9      64  682.24
    73.2  686.64    82.3  691.79    91.9  694.72   101.5  694.76     111  694.35
   120.6  693.12
#Mann= 3 , 0 , 0
       0      .1       0    45.7    .045       0      64     .07       0
Bank Sta=45.7,64
XS Rating Curve= 0 ,0
Exp/Cntr=0.3,0.1

Type RM Length L Ch R = 1 ,2143.3  ,67.9,60.9,73.6
XS GIS Cut Line= 4
     1834542.869      426353.291     1834522.904      426299.471
     1834482.105      426203.117     1834455.195      426165.791
#Sta/Elev= 26
       0  685.93     9.6  685.64    19.1  685.14    28.7  685.24    38.3  684.94
    47.8  684.14    57.4  683.64    66.9  681.83    76.4  679.57    84.6  678.65
    85.9   678.5    95.4  677.98    99.6  678.27     105  678.64  106.07  678.78
   114.5  679.82     124  681.87   133.5   684.3     143  686.63   152.5  688.86
     162  690.57   171.2  691.54   180.4  692.28   189.6   693.3   198.8  693.73
     208  694.07
#Mann= 3 , 0 , 0
       0      .1       0    84.6    .045       0  106.07     .08       0
Bank Sta=84.6,106.07
XS Rating Curve= 0 ,0
Exp/Cntr=0.3,0.1

Type RM Length L Ch R = 1 ,2082.4  ,80.1,117.3,147.5
XS GIS Cut Line= 4
     1834600.161      426346.346     1834580.195      426292.527
     1834539.397      426196.173     1834512.487      426158.846
#Sta/Elev= 27
       0  684.66     9.6  683.58    19.1  683.04    28.7  682.75    38.3  682.27
    47.8  680.54    57.4  677.07    66.9  674.25   73.52  673.57    75.4  673.41
    76.4  673.31    85.9  673.38    90.4  673.63   92.34   673.7    95.4  673.91
     105  675.11   114.5  675.85     124  677.66   133.5  678.77     143  679.44
   152.5  680.75     162  681.91   171.2  682.99   180.4  683.48   189.6  683.81
   198.8   683.9     208   683.9
#Mann= 3 , 0 , 0
       0      .1       0   73.52    .045       0   92.34      .1       0
Bank Sta=73.52,92.34
XS Rating Curve= 0 ,0
Exp/Cntr=0.3,0.1

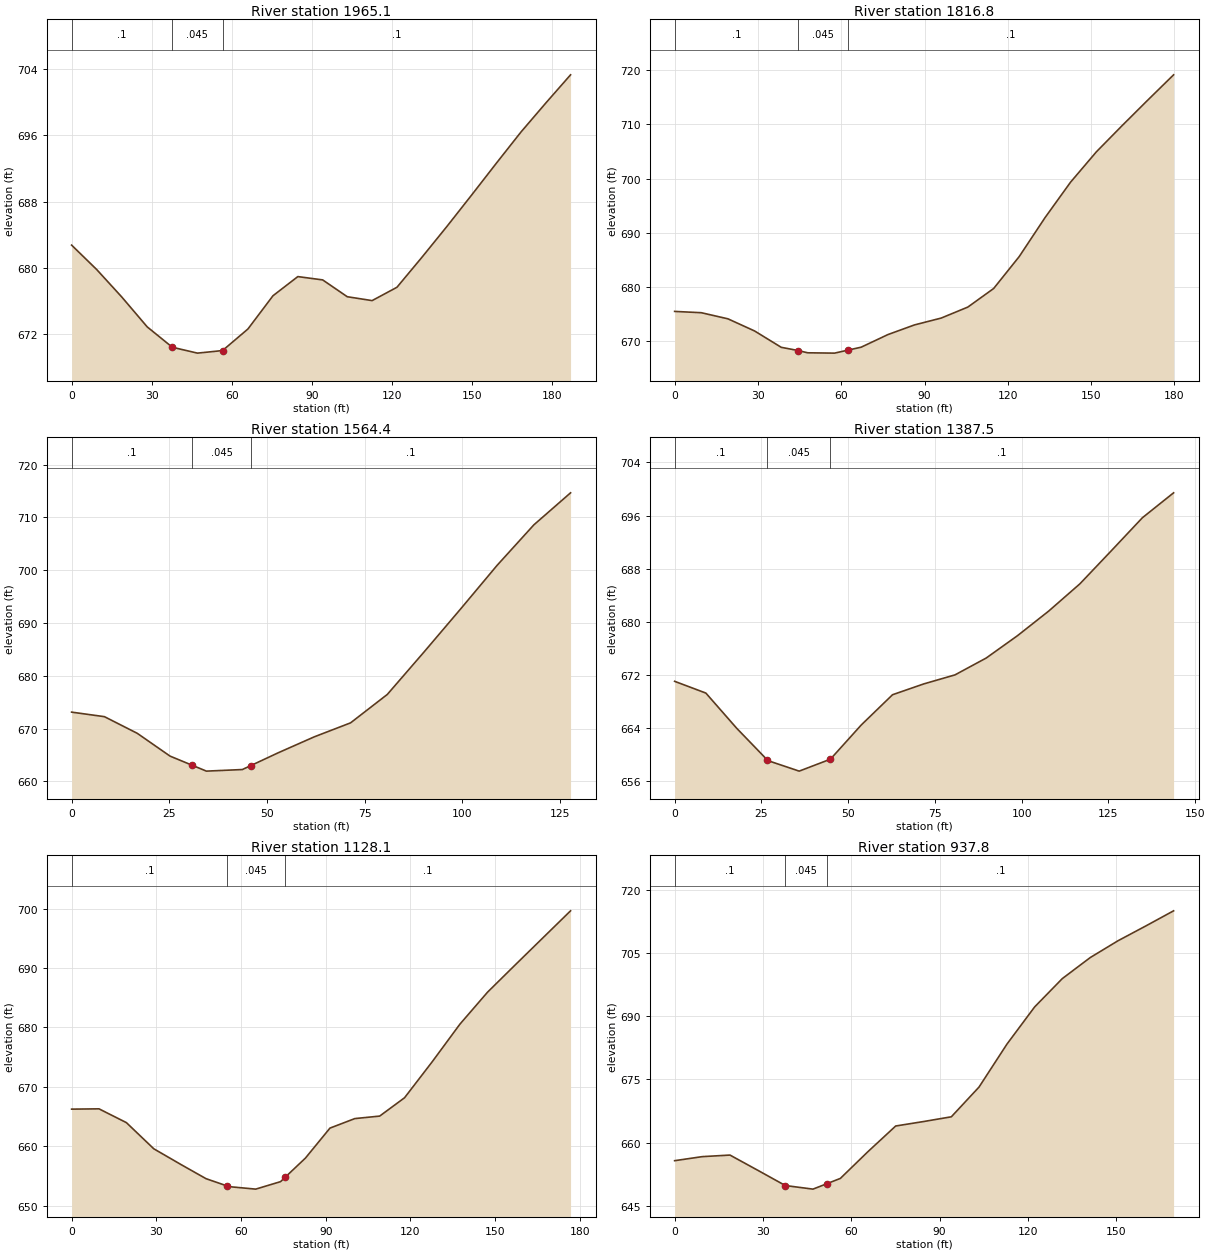
Type RM Length L Ch R = 1 ,1965.1  ,143.4,148.3,153
XS GIS Cut Line= 3
     1834628.806      426365.444     1834687.834      426318.569
     1834776.376       426250.86
#Sta/Elev= 23
       0  682.74     9.4  679.79    18.8  676.47    28.3  672.87    36.4  670.75
    37.7  670.41    47.1   669.7    51.4  669.84    56.5  670.01      66  672.61
    75.4  676.63    84.7  678.94      94  678.54   103.2  676.51   112.5  676.04
   121.8  677.65   131.1  681.25   140.4  684.95   149.7  688.76     159  692.62
   168.3  696.42   177.6  699.92   186.8   703.3
#Mann= 3 , 0 , 0
       0      .1       0    37.7    .045       0    56.5      .1       0
Bank Sta=37.7,56.5
XS Rating Curve= 0 ,0
Exp/Cntr=0.3,0.1

Type RM Length L Ch R = 1 ,1816.8  ,244,252.4,258
XS GIS Cut Line= 3
     1834699.987      426482.631     1834794.605      426435.756
     1834866.654      426453.117
#Sta/Elev= 23
       0  675.49     9.6  675.25    19.2  674.12    28.8  671.88    38.4  668.86
   44.46  668.27    47.5   667.9      48  667.85    57.6  667.79    62.5  668.35
    67.2  668.89    76.8  671.21    86.4     673      96  674.26   105.6  676.29
   114.9  679.72   124.1  685.61   133.4   692.8   142.6  699.35   151.9  704.95
   161.2   709.8   170.4  714.49   179.7  719.16
#Mann= 3 , 0 , 0
       0      .1       0   44.46    .045       0    62.5      .1       0
Bank Sta=44.46,62.5
XS Rating Curve= 0 ,0
Exp/Cntr=0.3,0.1

Type RM Length L Ch R = 1 ,1564.4  ,174.4,176.9,182
XS GIS Cut Line= 4
     1834805.022      426692.701     1834830.195      426694.437
     1834875.334      426684.888     1834928.286      426665.791
#Sta/Elev= 17
       0  673.13     8.4  672.27    16.8  669.12    25.2   664.8    30.9  663.06
    34.5  661.96    43.7  662.26    45.9  663.02    52.9  665.44    62.1  668.45
    71.4   671.1    80.8  676.48    90.1  684.43    99.5  692.61   108.9  700.92
   118.3  708.58   127.7  714.65
#Mann= 3 , 0 , 0
       0      .1       0    30.9    .045       0    45.9      .1       0
Bank Sta=30.9,45.9
XS Rating Curve= 0 ,0
Exp/Cntr=0.3,0.1

Type RM Length L Ch R = 1 ,1387.5  ,260.8,259.4,257.8
XS GIS Cut Line= 3
     1834818.911       426867.18      1834899.64      426868.916
     1834957.799      426893.221
#Sta/Elev= 19
       0  671.03       9  669.26    17.9  663.95    26.6  659.24    26.9  659.08
    35.9   657.5    41.6  658.64    44.9   659.3    53.8  664.46    62.8  669.01
    71.8  670.64    80.8     672    89.8  674.54    98.8   677.9   107.8  681.61
   116.8  685.72   125.8  690.67   134.8  695.67   143.8  699.43
#Mann= 3 , 0 , 0
       0      .1       0    26.6    .045       0    44.9      .1       0
Bank Sta=26.6,44.9
XS Rating Curve= 0 ,0
Exp/Cntr=0.3,0.1

Type RM Length L Ch R = 1 ,1128.1  ,198.1,190.3,182.4
XS GIS Cut Line= 4
     1834796.341      427144.958     1834831.063      427127.596
     1834910.056      427124.124     1834968.216      427132.805
#Sta/Elev= 23
       0  666.25     9.7   666.3    19.4  663.98    29.1  659.58    38.8  656.91
    47.6  654.55   55.09  653.32    56.4  653.18    60.7  652.99    65.2  652.79
      74  654.05    75.7  654.82    82.8  658.01    91.5  663.06   100.3  664.66
   109.1  665.08   117.9  668.16   127.7  674.22   137.5  680.54   147.3  685.93
   157.1  690.52   166.9  695.07   176.7  699.62
#Mann= 3 , 0 , 0
       0      .1       0   55.09    .045       0    75.7      .1       0
Bank Sta=55.09,75.7
XS Rating Curve= 0 ,0
Exp/Cntr=0.3,0.1

Type RM Length L Ch R = 1 ,937.8   ,225.6,225,223.7
XS GIS Cut Line= 3
     1834852.765      427327.249     1834922.209      427298.603
     1835007.279      427257.805
#Sta/Elev= 21
       0  655.74     9.4   656.7    18.8  657.07    28.2  653.48    36.8  650.16
    37.6  649.85      47     649    51.8  650.31    56.3  651.54    65.7   657.9
    75.1  663.96    84.6  665.02      94  666.14   103.4  673.18   112.9  683.37
   122.3  692.18   131.7  698.89   141.2  703.88   150.6  707.85     160  711.34
   169.5  714.95
#Mann= 3 , 0 , 0
       0      .1       0    37.6    .045       0    51.8      .1       0
Bank Sta=37.6,51.8
XS Rating Curve= 0 ,0
Exp/Cntr=0.3,0.1

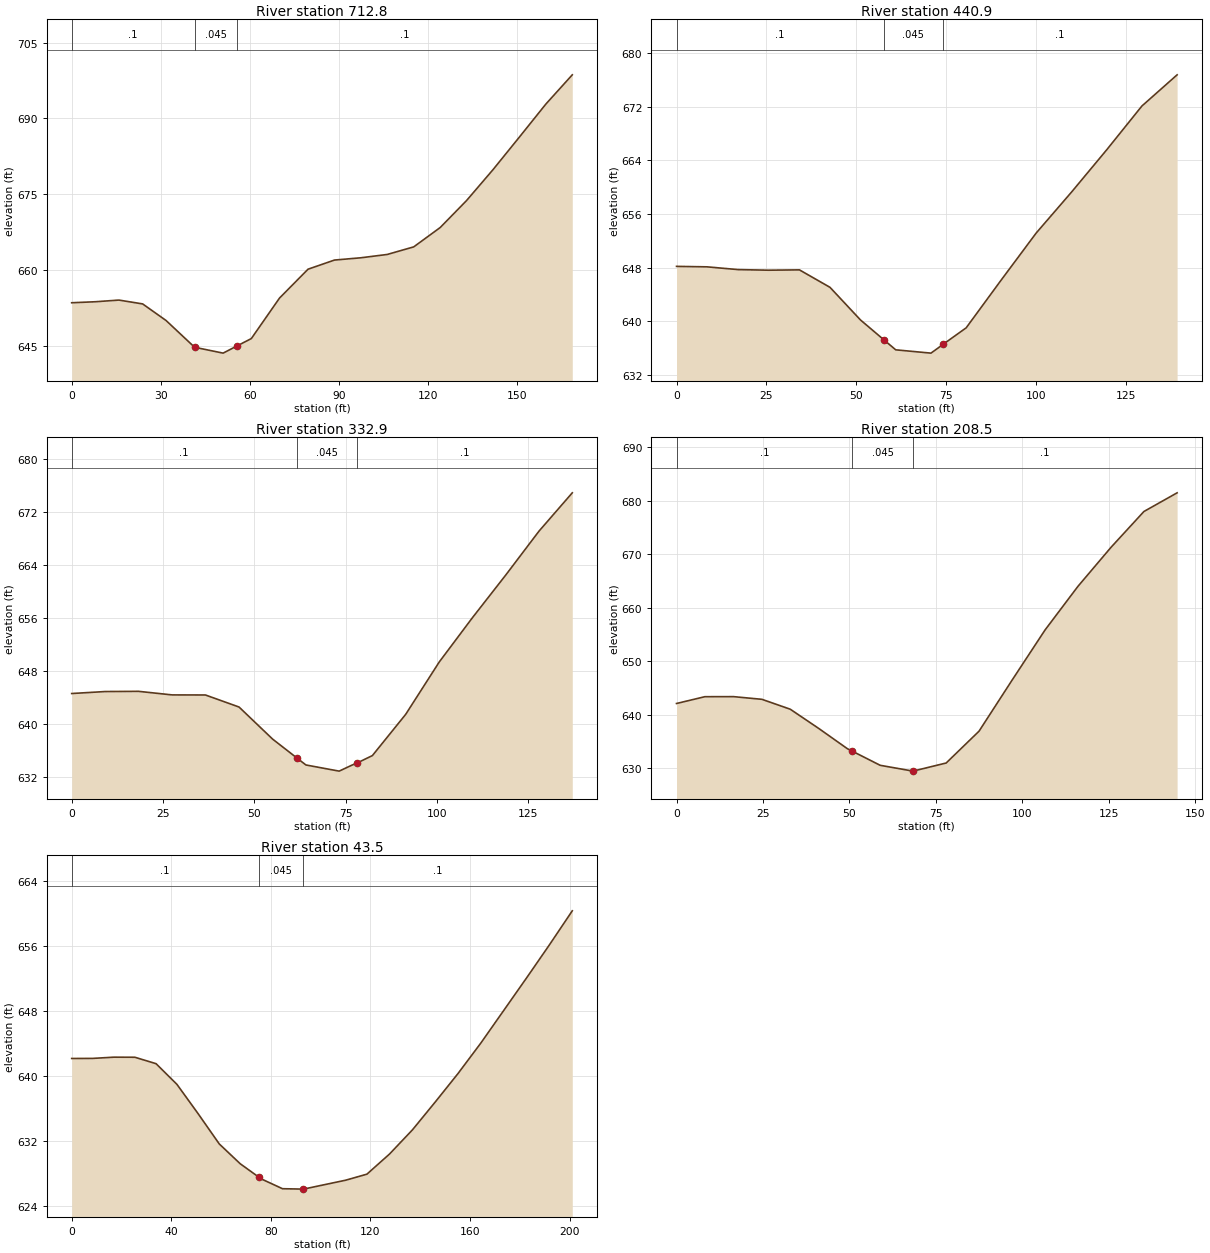
Type RM Length L Ch R = 1 ,712.8   ,262.3,271.9,280.4
XS GIS Cut Line= 4
     1834924.813      427542.527     1834953.459      427528.638
     1834996.862      427508.673     1835077.591      427471.346
#Sta/Elev= 22
       0  653.52       8  653.72    15.9  654.05    23.9  653.29    31.8     650
    40.8  645.04    41.4  644.71      51  643.55    55.8  645.01    60.5  646.43
      70  654.45    79.6  660.16    88.5  661.97    97.4  662.42   106.3  663.08
   115.2  664.58   124.1   668.4     133  673.75   141.9  679.86   150.8  686.32
   159.7  692.84   168.6  698.63
#Mann= 3 , 0 , 0
       0      .1       0    41.4    .045       0    55.8      .1       0
Bank Sta=41.4,55.8
XS Rating Curve= 0 ,0
Exp/Cntr=0.3,0.1

Type RM Length L Ch R = 1 ,440.9   ,115.5,108,99.8
XS GIS Cut Line= 4
     1835012.487      427764.749     1835063.702      427765.617
     1835102.765      427763.881     1835151.376      427757.805
#Sta/Elev= 19
       0   648.2     8.5  648.13    17.1  647.72    25.6  647.63    34.2  647.68
    42.7  645.08    51.2  640.21    57.6   637.3      61  635.76    70.8  635.27
    72.6  635.96   74.15  636.57    80.6  639.04    90.3  646.13   100.1  653.18
   109.9  659.26   119.7  665.57   129.5   672.1   139.3  676.75
#Mann= 3 , 0 , 0
       0      .1       0    57.6    .045       0   74.15      .1       0
Bank Sta=57.6,74.15
XS Rating Curve= 0 ,0
Exp/Cntr=0.3,0.1

Type RM Length L Ch R = 1 ,332.9   ,122.4,124.3,127.3
XS GIS Cut Line= 3
     1835031.584      427890.617     1835084.536       427875.86
     1835160.056      427843.742
#Sta/Elev= 19
       0  644.54     9.2  644.84    18.3  644.87    27.5  644.33    36.6  644.32
    45.8   642.5      55  637.65    61.6  634.82    64.1  633.75    73.2  632.82
    76.6   633.7      78  634.02    82.3  635.17    91.4  641.39   100.6  649.31
   109.7  656.01   118.8  662.44   127.9  669.07     137  674.85
#Mann= 3 , 0 , 0
       0      .1       0    61.6    .045       0      78      .1       0
Bank Sta=61.6,78
XS Rating Curve= 0 ,0
Exp/Cntr=0.3,0.1

Type RM Length L Ch R = 1 ,208.5   ,165.4,165,163.8
XS GIS Cut Line= 4
     1835075.855      428006.069      1835122.73      427990.444
     1835168.737      427978.291      1835212.14      427958.326
#Sta/Elev= 19
       0  642.13     8.2   643.4    16.5  643.41    24.7  642.91    32.9  641.06
    41.2  637.44    49.4  633.69    50.9   633.2    58.9  630.58    65.9  629.78
    68.4  629.49      78  631.01    87.5  636.95      97  646.43   106.6  655.87
   116.1  664.01   125.7  671.33   135.2  678.01   144.8   681.5
#Mann= 3 , 0 , 0
       0      .1       0    50.9    .045       0    68.4      .1       0
Bank Sta=50.9,68.4
XS Rating Curve= 0 ,0
Exp/Cntr=0.3,0.1

Type RM Length L Ch R = 1 ,43.5    ,43.1,43.5,43.8
XS GIS Cut Line= 4
     1835097.556      428124.124     1835147.904      428155.374
     1835204.327      428137.145     1835235.577      428060.756
#Sta/Elev= 26
       0  642.13     8.5  642.14    16.9  642.29    25.4  642.28    33.9  641.49
    42.3  638.94    50.8  635.34    59.3  631.62    67.7  629.19    75.1  627.56
    76.2  627.32    84.7  626.12    90.1  626.09    93.1  626.07   101.6  626.62
   110.1  627.17   118.6  627.91   127.7  630.39   136.9  633.36   146.1   636.8
   155.2  640.28   164.4  644.04   173.6  648.05   182.8  652.06   191.9  656.09
   201.1  660.28
#Mann= 3 , 0 , 0
       0      .1       0    75.1    .045       0    93.1      .1       0
Bank Sta=75.1,93.1
XS Rating Curve= 0 ,0
Exp/Cntr=0.3,0.1

Chan Stop Cuts=-1
Use User Specified Reach Order=0
Composite Channel Slope=5